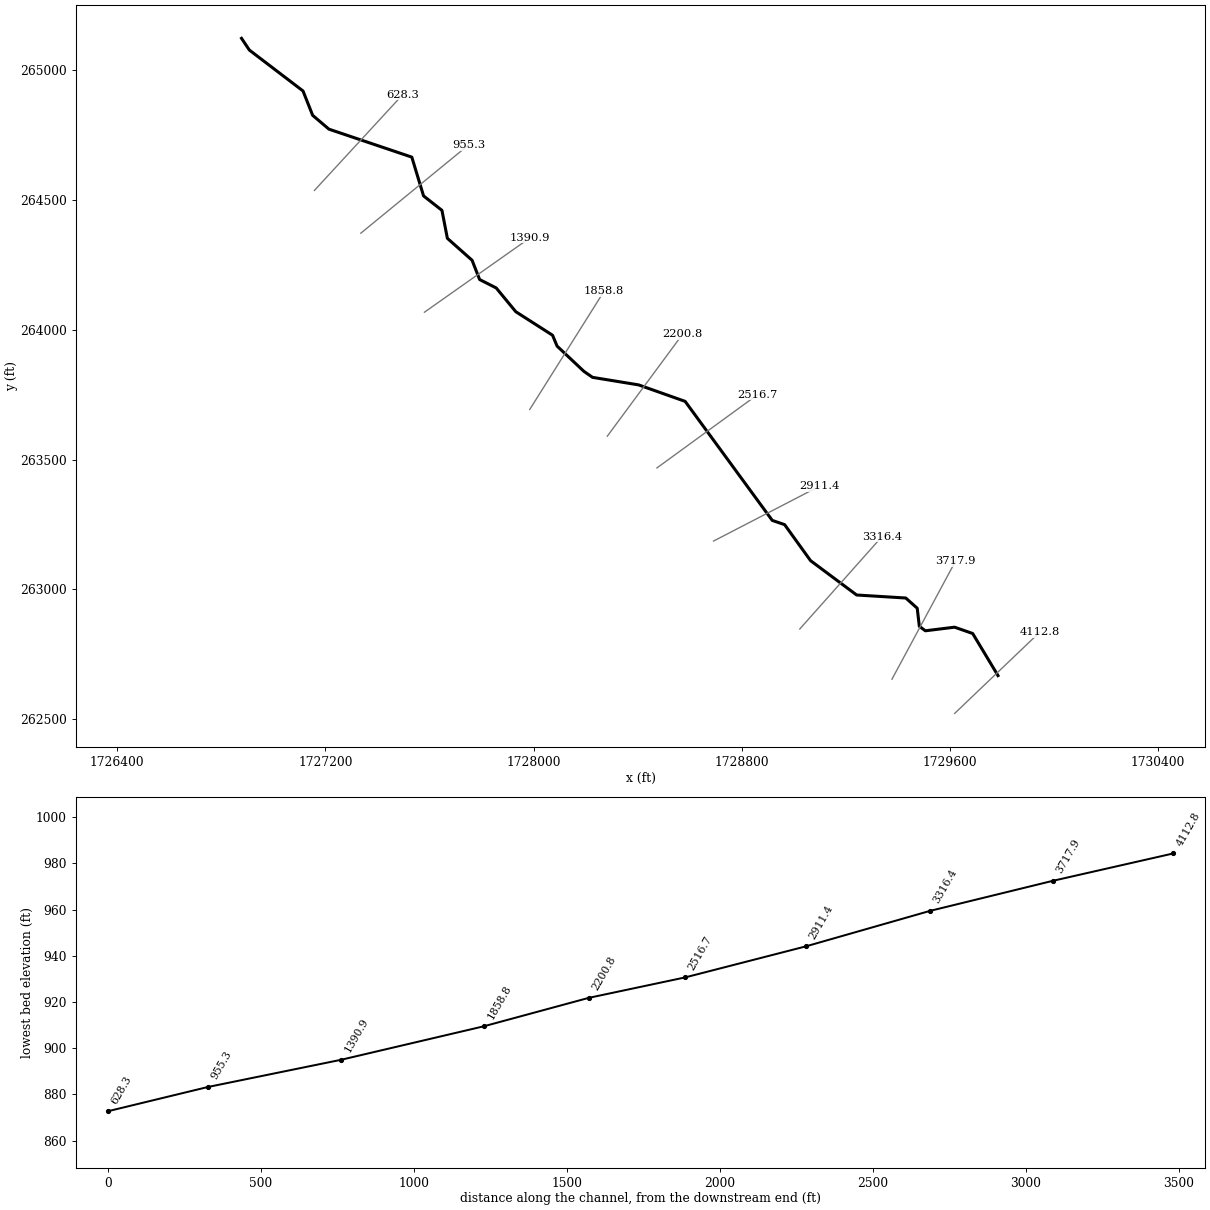
--- BIGSPRGBRN.prj (project) ---

Proj Title=BIGSPRGBRN
Current Plan=p01
Default Exp/Contr=0,0
English Units
Geom File=g01
Flow File=f01
Plan File=p01
BEGIN DESCRIPTION:
END DESCRIPTION:
DSS Export Rating Curves= 0
DSS Export Rating Curve Sorted= 0
DSS Export Volume Flow Curves= 0
DXF OffsetX= 0
DXF OffsetY= 0
DXF ScaleX= 0
DXF ScaleY= 0

--- BIGSPRGBRN.p01 (plan) ---

Plan Title=Floodplain
Program Version=4.00
Geom File=g01
Flow File=f01
K Sum by GR=0
Std Step Tol=0.01
Critical Tol=0.01
Num of Std Step Trials=20
Max Error Tol=0.3
Flow Tol Ratio=0.001
Split Flow NTrial=30
Split Flow Tol=0.02
Split Flow Ratio=0.02
Log Output Level=0
Friction Slope Method=1
Unsteady Friction Slope Method=2
Unsteady Bridges Friction Slope Method=1
Global Log Level=0
CheckData=False
Run HTab=0
Run UNet=0
Run PostProcess=0
UNET Theta=0
UNET Theta Warmup=0
UNET ZTol=0
UNET ZSATol=0
UNET MxIter=0
UNET MaxInSteps=0
UNET DtIC=0
UNET DtMin=0
UNET MaxCRTS=0
UNET WFStab=0
UNET SFStab=0
UNET WFX=0
UNET SFX=0
UNET DSS MLevel=0
UNET DZMax Abort=0
UNET Convert EG Bridges=0
UNET Use Existing IB Tables=0
UNET Froude Limit=0
UNET Froude Power=0
Write IC File=0
Echo Input=False
Echo Output=False
Write Detailed=0

--- BIGSPRGBRN.f01 (steady flow) ---

Flow Title=NFF Regression Equation
Program Version=4.10
Number of Profiles= 1
Profile Names=P100yr
River Rch & RM=BIGSPRGBRN,Main            ,4112.8
 938.921
River Rch & RM=BIGSPRGBRN,Main            ,2200.8
1013.337
Boundary for River Rch & Prof#=BIGSPRGBRN,Main            , 1
Up Type= 0
Dn Type= 1
Dn Known WS=876.31
DSS Import GetInterval= 0
DSS Import GetPeak= 0
DSS Import FillOption= 0

--- BIGSPRGBRN.g01 (geometry) ---

Geom Title=USGS 10m DEM
Program Version=4.00

River Reach=BIGSPRGBRN     ,Main
Reach XY= 30
     1729784.475      262668.208     1729687.186      262830.357
     1729617.693      262854.679     1729505.348      262840.780
     1729482.184      262858.153     1729474.076      262927.646
     1729430.064      262967.025     1729241.277      262978.607
     1729064.266      263110.825     1728964.467      263249.626
     1728916.980      263265.841     1728582.190      263724.317
     1728403.216      263787.821     1728226.356      263816.815
     1728193.014      263840.009     1728090.087      263937.137
     1728072.706      263978.974     1727931.349      264069.634
     1727856.066      264161.132     1727792.365      264193.561
     1727763.410      264267.687     1727668.438      264352.235
     1727647.590      264459.948     1727576.939      264515.542
     1727531.770      264664.950     1727213.264      264772.663
     1727150.721      264825.940     1727113.658      264919.755
     1726907.498      265077.271     1726877.385      265122.441

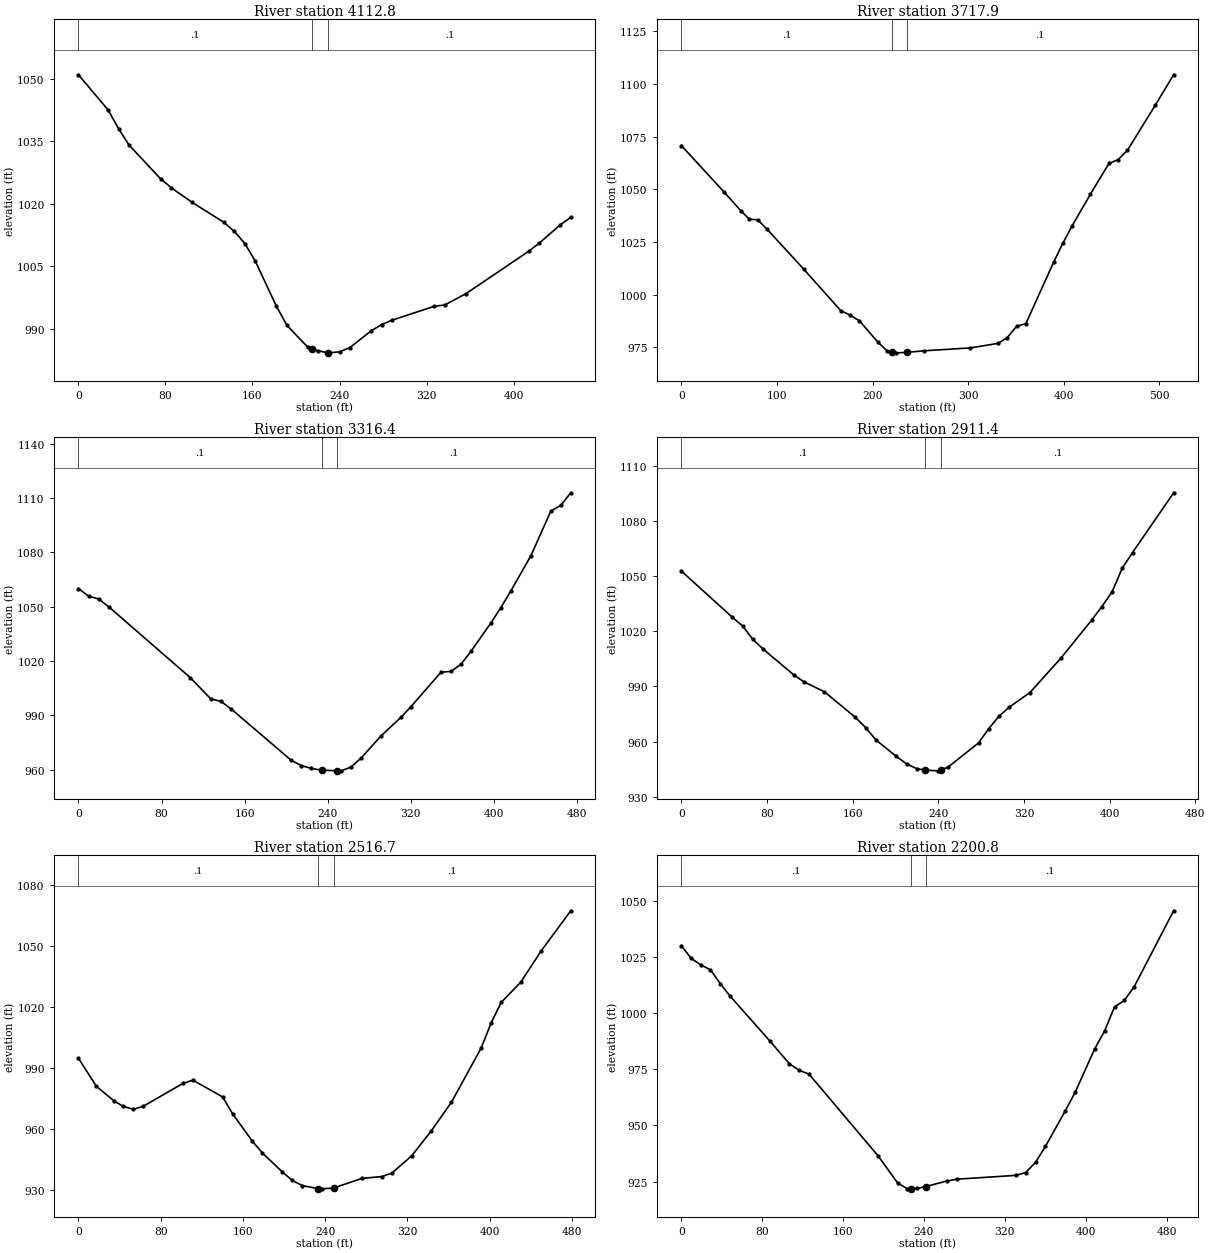
Type RM Length L Ch R = 1 ,4112.8,387.5,394.8,404.5
XS GIS Cut Line= 3
     1729618.149      262522.739     1729630.882      262534.925
     1729945.152      262835.691
#Sta/Elev= 30
       0 1050.93    27.3 1042.48    37.0 1037.94    46.6 1034.05    75.6 1025.97
    85.3 1023.86   104.6 1020.33   133.6 1015.58   143.3 1013.38   153.0 1010.47
   162.6 1006.24   182.0  995.45   191.6  990.88   211.0  985.58   214.6  985.26
   220.6  984.73   229.6  984.31   230.3  984.28   240.0  984.52   249.6  985.55
   269.0  989.54   278.6  991.03   288.3  992.11   327.0  995.43   336.6  995.75
   356.0  998.42   414.0 1008.64   423.6 1010.58   443.0 1014.97   452.6 1016.76
#Mann= 3 , 0 , 0
       0     0.1       0   214.6   0.045       0   229.6     0.1       0
Bank Sta=   214.6,   229.6
Exp/Cntr=0.3,0.1

Type RM Length L Ch R = 1 ,3717.9,406.2,401.4,394.2
XS GIS Cut Line= 3
     1729376.999      262654.298     1729414.818      262724.714
     1729620.636      263107.931
#Sta/Elev= 30
       0 1070.76    44.4 1048.86    62.2 1039.82    71.0 1035.88    79.9 1035.47
    89.6 1031.09   128.3 1011.95   166.9  992.34   176.6  990.30   186.3  987.57
   205.6  977.46   215.3  973.30   220.5  972.81   224.9  972.40   235.5  972.59
   253.9  973.37   302.3  974.74   331.3  976.89   340.9  979.65   350.6  985.01
   360.3  986.25   389.3 1015.32   398.9 1024.32   408.6 1032.55   427.9 1047.77
   447.2 1062.25   456.9 1064.11   466.6 1068.55   495.6 1089.85   514.9 1104.35
#Mann= 3 , 0 , 0
       0     0.1       0   220.5   0.045       0   235.5     0.1       0
Bank Sta=   220.5,   235.5
Exp/Cntr=0.3,0.1

Type RM Length L Ch R = 1 ,3316.4,413.5,404.8,396
XS GIS Cut Line= 3
     1729022.735      262847.712     1729126.864      262965.005
     1729337.646      263202.436
#Sta/Elev= 30
       0 1060.00     9.8 1055.79    19.6 1054.25    29.4 1049.81   107.8 1010.80
   127.4  999.15   137.2  997.72   147.0  993.62   205.0  965.18   214.6  962.33
   224.2  960.75   234.3  959.75   249.3  959.46   253.1  959.39   262.7  961.50
   272.3  966.44   291.5  978.67   310.8  988.96   320.4  994.84   349.3 1013.85
   358.9 1014.28   368.5 1018.18   378.1 1025.30   397.4 1041.05   407.0 1049.52
   416.6 1058.71   435.9 1078.12   455.1 1102.74   464.7 1105.90   474.3 1112.86
#Mann= 3 , 0 , 0
       0     0.1       0   234.3   0.045       0   249.3     0.1       0
Bank Sta=   234.3,   249.3
Exp/Cntr=0.3,0.1

Type RM Length L Ch R = 1 ,2911.4,390.4,394.4,398.4
XS GIS Cut Line= 3
     1728691.453      263186.387     1728801.640      263243.550
     1729099.701      263398.178
#Sta/Elev= 30
       0 1052.68    47.7 1027.52    57.3 1022.79    66.8 1015.51    76.4 1010.28
   105.0  996.25   114.6  992.43   133.7  987.04   162.5  973.20   172.1  967.62
   181.7  960.89   200.9  951.90   210.5  947.81   220.1  945.21   227.6  944.48
   239.3  944.07   242.6  944.72   248.8  945.95   277.6  959.22   287.2  967.03
   296.8  973.79   306.4  978.73   325.6  986.60   354.4 1005.21   383.2 1025.94
   392.8 1033.31   402.4 1041.40   412.0 1054.38   421.5 1062.75   459.9 1095.24
#Mann= 3 , 0 , 0
       0     0.1       0   227.6   0.045       0   242.6     0.1       0
Bank Sta=   227.6,   242.6
Exp/Cntr=0.3,0.1

Type RM Length L Ch R = 1 ,2516.7,309,315.7,322.4
XS GIS Cut Line= 3
     1728473.796      263468.017     1728508.945      263493.671
     1728860.707      263750.407
#Sta/Elev= 30
       0  994.89    17.4  981.06    34.8  973.81    43.5  971.22    53.2  969.76
    62.9  971.21   101.6  982.48   111.3  984.11   140.3  975.84   150.0  967.52
   169.3  954.01   179.0  948.25   198.4  938.95   208.0  934.79   217.7  932.25
   233.2  930.76   237.1  930.64   248.2  931.05   275.8  935.78   295.1  936.68
   304.8  938.33   324.2  946.85   343.5  959.28   362.9  973.24   391.9  999.97
   401.6 1012.36   411.3 1022.33   430.6 1032.45   450.0 1047.53   479.0 1067.42
#Mann= 3 , 0 , 0
       0     0.1       0   233.2   0.045       0   248.2     0.1       0
Bank Sta=   233.2,   248.2
Exp/Cntr=0.3,0.1

Type RM Length L Ch R = 1 ,2200.8,340.3,342,343.6
XS GIS Cut Line= 3
     1728283.116      263590.339     1728300.182      263613.497
     1728571.995      263982.362
#Sta/Elev= 30
       0 1030.04     9.6 1024.44    19.2 1021.50    28.8 1019.29    38.5 1013.16
    48.3 1007.54    87.3  987.74   106.8  977.49   116.5  974.57   126.3  972.84
   194.5  936.52   214.0  924.37   223.7  921.77   227.1  921.83   233.5  921.95
   242.1  922.81   262.7  925.27   272.5  926.07   331.0  927.77   340.7  929.03
   350.5  933.66   360.2  940.70   379.7  956.39   389.5  964.70   409.0  984.20
   418.7  992.08   428.5 1002.80   438.2 1005.64   448.0 1011.79   487.0 1045.58
#Mann= 3 , 0 , 0
       0     0.1       0   227.1   0.045       0   242.1     0.1       0
Bank Sta=   227.1,   242.1
Exp/Cntr=0.3,0.1

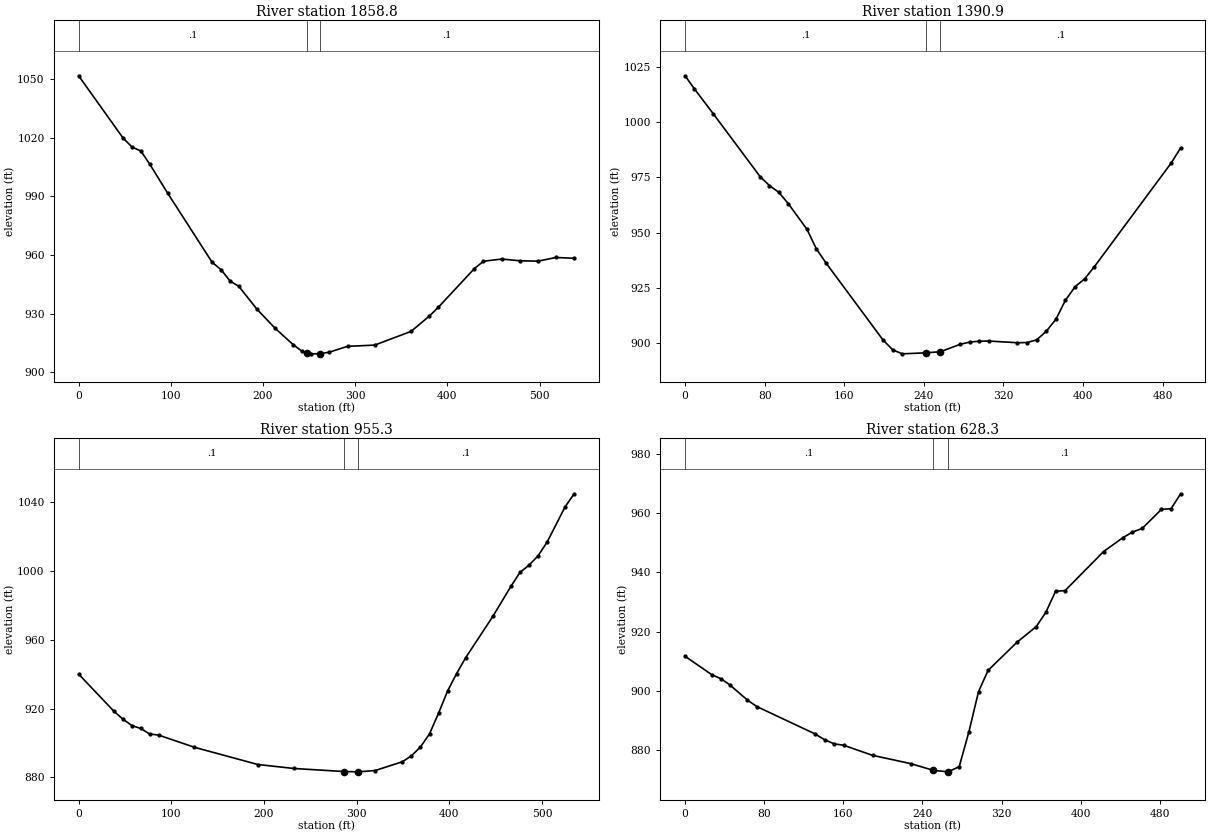
Type RM Length L Ch R = 1 ,1858.8,475.4,467.3,459.2
XS GIS Cut Line= 3
     1727984.960      263693.153     1728082.504      263848.649
     1728270.639      264148.559
#Sta/Elev= 30
       0 1051.57    48.3 1019.69    58.0 1015.16    67.6 1013.11    77.3 1006.30
    96.6  991.58   144.9  956.22   154.6  952.49   164.2  946.72   173.9  943.95
   193.4  932.34   213.1  922.58   232.7  914.23   242.6  910.71   247.3  910.13
   252.4  909.50   262.3  909.58   272.1  910.38   291.7  913.32   321.2  913.97
   360.6  920.95   380.2  928.68   390.1  933.23   429.4  953.08   439.2  956.81
   458.9  957.93   478.6  957.05   498.3  956.85   517.9  958.73   537.6  958.33
#Mann= 3 , 0 , 0
       0     0.1       0   247.3   0.045       0   262.3     0.1       0
Bank Sta=   247.3,   262.3
Exp/Cntr=0.3,0.1

Type RM Length L Ch R = 1 ,1390.9,432.5,435.5,442.5
XS GIS Cut Line= 3
     1727580.273      264067.667     1727703.439      264154.653
     1727987.151      264355.027
#Sta/Elev= 30
       0 1021.15     9.4 1015.18    28.3 1003.94    75.4  975.40    84.8  971.32
    94.2  968.28   103.7  963.14   122.5  951.49   131.9  942.65   141.4  936.36
   199.0  901.23   208.7  896.79   218.3  894.98   241.7  895.43   256.7  895.95
   276.2  899.25   285.9  900.30   295.5  900.70   305.2  900.79   334.1  900.02
   343.8  900.10   353.4  901.33   363.0  905.20   372.7  910.63   382.3  919.30
   392.0  925.45   401.6  928.99   411.3  934.47   488.5  981.49   498.1  988.42
#Mann= 3 , 0 , 0
       0     0.1       0   241.7   0.045       0   256.7     0.1       0
Bank Sta=   241.7,   256.7
Exp/Cntr=0.3,0.1

Type RM Length L Ch R = 1 ,955.3,324.9,326.6,324.3
XS GIS Cut Line= 3
     1727335.885      264372.089     1727409.909      264432.847
     1727749.100      264711.250
#Sta/Elev= 30
       0  940.08    38.3  918.32    47.9  913.83    57.5  910.11    67.0  908.43
    76.6  905.22    86.2  904.60   125.0  897.48   193.3  887.47   232.3  885.15
   286.6  883.37   300.6  883.20   301.6  883.22   320.0  883.97   349.3  889.09
   359.1  892.56   368.8  897.67   378.6  905.35   388.3  917.35   398.1  930.33
   407.8  940.40   417.6  949.68   446.8  973.61   466.3  991.07   476.1  999.25
   485.8 1003.42   495.6 1008.88   505.3 1016.79   524.8 1037.41   534.6 1045.01
#Mann= 3 , 0 , 0
       0     0.1       0   286.6   0.045       0   301.6     0.1       0
Bank Sta=   286.6,   301.6
Exp/Cntr=0.3,0.1

Type RM Length L Ch R = 1 ,628.3,636.5,628.4,620.2
XS GIS Cut Line= 3
     1727157.458      264536.647     1727200.175      264583.089
     1727496.698      264905.466
#Sta/Elev= 30
       0  911.70    27.0  905.49    36.1  904.15    45.1  902.10    63.1  896.91
    72.8  894.70   131.2  885.55   141.0  883.56   150.7  882.17   160.4  881.68
   189.6  878.28   228.6  875.46     251  873.22     266  872.72   277.2  874.49
   287.0  886.24   296.7  899.75   306.4  906.95   335.6  916.44   355.1  921.72
   364.8  926.53   374.6  933.61   384.3  933.88   423.2  947.04   442.7  951.72
   452.4  953.61   462.2  954.83   481.6  961.24   491.4  961.49   501.1  966.53
#Mann= 3 , 0 , 0
       0     0.1       0     251   0.045       0     266     0.1       0
Bank Sta=     251,     266
Exp/Cntr=0.3,0.1